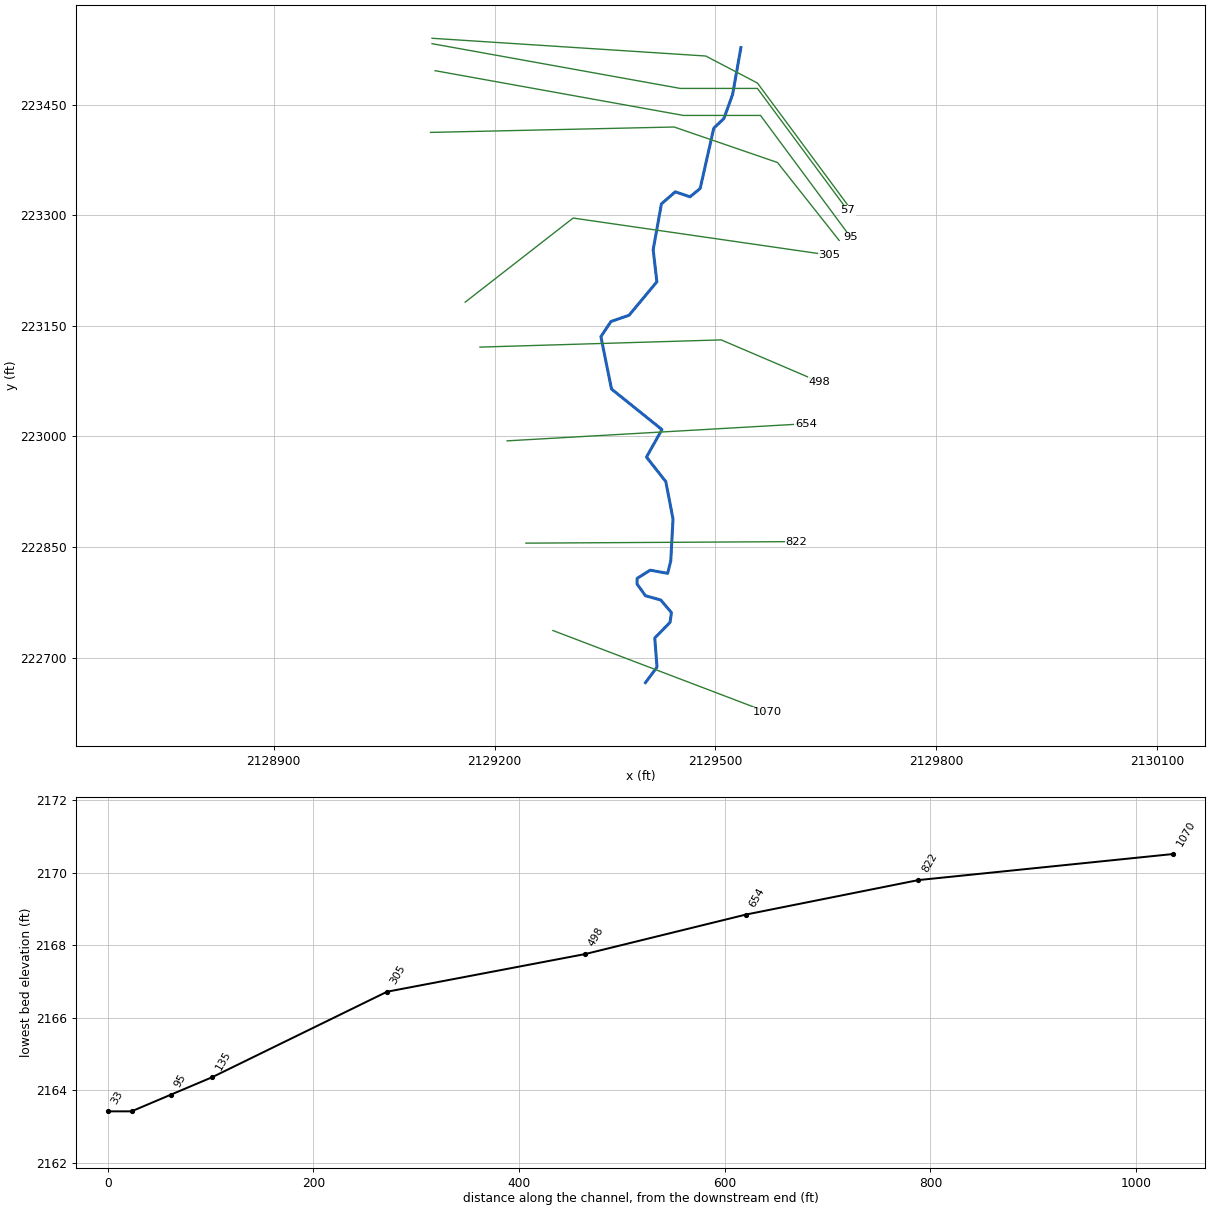
--- SECONDCKT2.prj (project) ---

Proj Title=SECONDCKT2
Current Plan=p01
Default Exp/Contr=0,0
English Units
Geom File=g01
Flow File=f01
Plan File=p01
Background Map Layer=Inundation Boundary (01pct Value_0)
BEGIN DESCRIPTION:
Stream Name: Second Creek Tributary 2
Flood Zone: Approximate
Monroe County, West Virginia
HEC-RAS Version: 5.0.7
Vertical Datum: NAVD88
Projection: NAD 1983 StatePlane West Virginia S FIPS 4702 (US Feet)
LiDAR: 2016, 1-meter
Land Use: 2016 NLCD
Hydrologic Method:
SIR2010-5033 regression equations
END DESCRIPTION:
DSS Export Rating Curves= 0
DSS Export Rating Curve Sorted= 0
DSS Export Volume Flow Curves= 0
DXF OffsetX= 0
DXF OffsetY= 0
DXF ScaleX= 0
DXF ScaleY= 0

--- SECONDCKT2.p01 (plan) ---

Plan Title=Floodplain
Program Version=5.07
Short Identifier=Floodplain
Geom File=g01
Flow File=f01
Subcritical Flow
K Sum by GR= 0
Std Step Tol= 0.01
Critical Tol= 0.01
Num of Std Step Trials= 20
Max Error Tol= 0.3
Flow Tol Ratio= 0.001
Split Flow NTrial= 30
Split Flow Tol= 0.02
Split Flow Ratio= 0.02
Log Output Level= 0
Friction Slope Method= 1
Unsteady Friction Slope Method= 2
Unsteady Bridges Friction Slope Method= 1
Parabolic Critical Depth
Global Vel Dist= 0 , 0 , 0
Global Log Level= 0
CheckData=True
Encroach Param=-1 ,0,0, 0
Mapping Interval=1HOUR
Computation Time Step Use Courant=        0
Computation Time Step Use Time Series=    0
Computation Time Step Count To Double=0
Computation Time Step Max Doubling=0
Computation Time Step Max Halving=0
Computation Time Step Residence Courant=0
Run HTab= 0
Run UNet= 0
Run Sediment= 0
Run PostProcess= 0
Run WQNet= 0
Run RASMapper=-1
UNET Theta= 0
UNET Theta Warmup= 0
UNET ZTol= 0
UNET ZSATol= 0
UNET MxIter= 0
UNET Max Iter WO Improvement= 0
UNET MaxInSteps= 0
UNET DtIC= 0
UNET DtMin= 0
UNET MaxCRTS= 0
UNET WFStab= 0
UNET SFStab= 0
UNET WFX= 1
UNET SFX= 1
UNET 1D Methodology=Finite Difference
UNET DSS MLevel= 1
UNET Pardiso=0
UNET DZMax Abort= 0
UNET Use Existing IB Tables= 0
UNET Froude Reduction=False
UNET Froude Limit= 0
UNET Froude Power= 0
UNET D1 Cores= 0
UNET D2 Coriolis=0
UNET D2 Cores= 0
UNET D2 Theta= 1
UNET D2 Theta Warmup= 1
UNET D2 Z Tol= 0.01
UNET D2 Volume Tol= 0.01
UNET D2 Max Iterations= 20
UNET D2 Equation= 0
UNET D2 RampUpFraction=0.1
UNET D2 TimeSlices= 1
UNET D2 BCVolumeCheck=0
UNET D1D2 MaxIter= 0
UNET D1D2 ZTol=0.01
UNET D1D2 QTol=0.1
UNET D1D2 MinQTol=1
Write IC File= 0
Write IC File at Fixed DateTime=0
Write IC File at Sim End=0
Echo Input=False
Echo Parameters=False
Echo Output=False
Write Detailed= 0
HDF Write Warmup=0
HDF Write Time Slices=0
HDF Flush=0
HDF Face Node Velocities=0
HDF Compression= 1
HDF Chunk Size= 1
HDF Spatial Parts= 1
HDF Use Max Rows=0
HDF Fixed Rows= 1
Calibration Method= 0
Calibration Iterations= 20
Calibration Max Change=0.05
Calibration Tolerance=0.2
Calibration Maximum=1.5
Calibration Minimum=0.5
Calibration Optimization Method= 1
WQ AD Non Conservative
WQ ULTIMATE=-1
WQ Max Comp Step=1HOUR
WQ Output Interval=15MIN
WQ Output Selected Increments= 0
WQ Output face flow=0
WQ Output face velocity=0
WQ Output face area=0
WQ Output face dispersion=0
WQ Output cell volume=0
WQ Output cell surface area=0
WQ Output cell continuity=0
WQ Output cumulative cell continuity=0
WQ Output face conc=0
WQ Output face dconc_dx=0
WQ Output face courant=0
WQ Output face peclet=0
WQ Output face adv mass=0
WQ Output face disp mass=0
WQ Output cell mass=0
WQ Output cell source sink temp=0
WQ Output nsm pathways=0
WQ Output nsm derived pathways=0
WQ Output MaxMinRange=-1
WQ Daily Max Min Mean=-1
WQ Daily Range=0
WQ Daily Time=0
WQ Create Restart=0
WQ Fixed Restart=0
WQ System Summary=0
WQ Write To DSS=0
WQ Use Fixed Temperature=0
Sorting and Armoring Iterations= 10
XS Update Threshold= 0.02
Bed Roughness Predictor= 0
Hydraulics Update Threshold= 0.02
Energy Slope Method= 1
Volume Change Method= 1
Sediment Retention Method= 0
XS Weighting Method= 0
Number of US Weighted Cross Sections= 1
Number of DS Weighted Cross Sections= 1
Upstream XS Weight=0
Main XS Weight=1
Downstream XS Weight=0
Number of DS XS's Weighted with US Boundary= 1
Upstream Boundary Weight= 1
Weight of XSs Associated with US Boundary= 0
Number of US XS's Weighted with DS Boundary= 1
Downstream Boundary Weight= 0.5
Weight of XSs Associated with DS Boundary= 0.5
Percentile Method= 0
Sediment Output Level= 3
Mass or Volume Output= 0
Output Increment Type= 1
Profile and TS Output Increment= 1
XS Output Flag= 0
XS Output Increment= 10
Write Gradation File= 0
Read Gradation Hotstart= 0
Write HDF5 File= 1
Write Binary Output= 1
Write DSS Sediment File= 0
SV Curve= 0
Specific Gage Flag= 0

--- SECONDCKT2.f01 (steady flow) ---

Flow Title=Flow
Program Version=5.07
Number of Profiles= 6
Profile Names=01pct,10pct,04pct,02pct,0_2pct,01plus
River Rch & RM=SECONDCKT2,Main            ,1070
     369     192     257     312     520     546
Boundary for River Rch & Prof#=SECONDCKT2,Main            , 1
Up Type= 0
Dn Type= 3
Dn Slope=0.006586
Boundary for River Rch & Prof#=SECONDCKT2,Main            , 2
Up Type= 0
Dn Type= 3
Dn Slope=0.006586
Boundary for River Rch & Prof#=SECONDCKT2,Main            , 3
Up Type= 0
Dn Type= 3
Dn Slope=0.006586
Boundary for River Rch & Prof#=SECONDCKT2,Main            , 4
Up Type= 0
Dn Type= 3
Dn Slope=0.006586
Boundary for River Rch & Prof#=SECONDCKT2,Main            , 5
Up Type= 0
Dn Type= 3
Dn Slope=0.006586
Boundary for River Rch & Prof#=SECONDCKT2,Main            , 6
Up Type= 0
Dn Type= 3
Dn Slope=0.006586
DSS Import GetInterval= 0
DSS Import GetPeak= 0
DSS Import FillOption= 0

--- SECONDCKT2.g01 (geometry) ---

Geom Title=Geometry
Program Version=5.07

River Reach=SECONDCKT2      ,Main
Reach XY= 30
     2129404.968      222665.959     2129420.585      222687.041
 2129417.5745794222726.533022687     2129438.325      222747.724
     2129440.189      222760.9442129425.79984543222777.991802153
2129404.90817627222783.8733123892129393.44831318 222799.85574977
      2129393.61      222807.3762129411.29279582222818.490443283
2129435.04314035222814.2539591762129439.30927647222831.318503657
2129442.33112289222888.0225629242129432.55456095222938.682929353
2129406.31782381 222971.983499132129427.31041312223009.303657911
     2129358.826      223064.3282129344.44498512223135.411411903
2129358.09617186223155.9304873532129382.66610604223164.368740704
2129420.40443979223209.828107851     2129415.401      223253.374
2129426.60224233223315.5069236732129445.40917109223331.841215621
2129465.44994958223325.1131134342129479.18274871223336.383860564
2129497.67762895223418.217304971  2129511.450861223431.392115377
2129523.25353608223464.029224328     2129534.527      223527.618

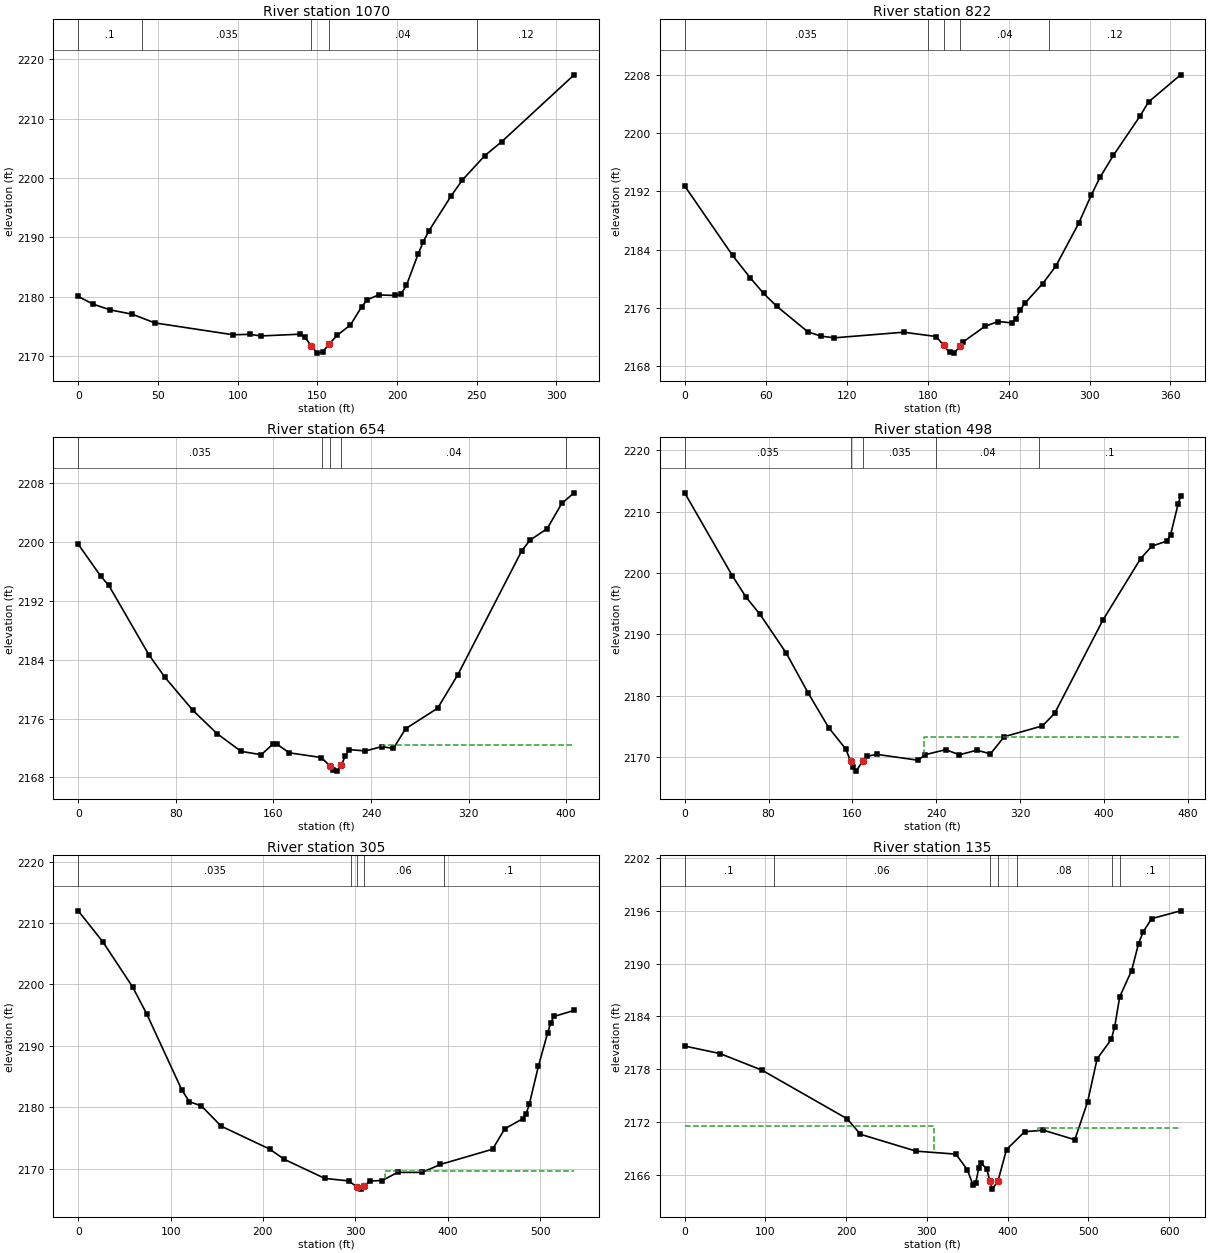
Type RM Length L Ch R = 1 ,1070    ,248,248,248
XS GIS Cut Line= 2
     2129279.268      222736.669     2129570.067      222625.992
#Sta/Elev= 30
       0 2180.06     9.3 2178.77      20  2177.8    33.9 2177.07      48 2175.61
    97.1 2173.61   107.6 2173.68   114.7 2173.41   139.2 2173.71     142 2173.24
   146.2 2171.78   149.8 2170.52   153.3 2170.71   157.3 2172.03   162.4 2173.51
   170.8 2175.27   177.8 2178.32   181.3 2179.49   188.4 2180.32   198.9 2180.22
   202.4 2180.43   205.9 2181.94   213.2 2187.17   216.5 2189.29     220  2191.1
     234    2197     241 2199.66   255.1 2203.77   265.6 2206.09   311.1 2217.36
#Mann= 5 ,-1 , 0
       0      .1       0      40    .035       0   146.2    .045       0
   157.3     .04       0     250     .12       0
Bank Sta=146.2,157.3
XS Rating Curve= 0 ,0
Exp/Cntr=0.3,0.1

Type RM Length L Ch R = 1 ,822     ,164.6,167.5,167.5
XS GIS Cut Line= 2
2129242.63171729222855.2040717662129610.07596869222857.297771204
#Sta/Elev= 30
       0 2192.75    35.5 2183.21    48.6 2180.13    58.5 2177.99    68.3 2176.22
    91.3 2172.72   101.1 2172.13     111  2171.9   162.2 2172.67   186.4 2172.08
   191.9 2170.85   196.3  2169.9   199.6  2169.8   203.9 2170.71   206.1 2171.31
   222.5 2173.48   232.4 2174.14   242.2 2173.95   245.5 2174.55   248.8 2175.77
   252.1 2176.66   265.2 2179.32     275 2181.73     292 2187.63   301.3  2191.5
   307.8 2193.94   317.7 2196.95   337.4 2202.33   343.7 2204.27   367.5    2208
#Mann= 5 ,-1 , 0
       0    .035       0     180     .04       0   191.9    .045       0
   203.9     .04       0     270     .12       0
Bank Sta=191.9,203.9
XS Rating Curve= 0 ,0
Exp/Cntr(USF)=0,0
Exp/Cntr=0.3,0.1

Type RM Length L Ch R = 1 ,654     ,156,156.4,156.7
XS GIS Cut Line= 2
2129217.00328527222993.9698178652129622.81910231223017.233144956
#Sta/Elev= 30
       0 2199.72    18.5 2195.36    25.1 2194.11      58 2184.66    71.1 2181.61
    94.1  2177.1   113.8 2173.95   133.5 2171.54     150 2171.08   159.8 2172.55
   163.1 2172.49     173 2171.34   199.3  2170.7   206.6 2169.51   209.1 2169.01
   212.4 2168.85   215.7 2169.64     219 2170.97   222.3 2171.77   235.4  2171.6
   248.6 2172.17   258.4 2171.95   268.3 2174.61   294.6 2177.41   311.2 2181.98
   363.6 2198.84   370.4 2200.28   384.4 2201.84   396.4 2205.28   406.5 2206.71
#Mann= 5 ,-1 , 0
       0    .035       0     200     .04       0   206.6    .045       0
   215.7     .04       0     400     .06       0
#XS Ineff= 2 , 0
                          249.27         2172.41
Permanent Ineff=
       F       F
Bank Sta=206.6,215.7
XS Rating Curve= 0 ,0
Exp/Cntr(USF)=0,0
Exp/Cntr=0.3,0.1

Type RM Length L Ch R = 1 ,498     ,195,192.8,192
XS GIS Cut Line= 3
2129180.27162824 223121.177945972129507.79487391 223130.96496629
2129641.31515058223073.891496393
#Sta/Elev= 30
       0 2213.05    45.4 2199.56    58.5 2196.08    71.7  2193.3      97 2186.93
   117.6 2180.51   137.3 2174.84   153.7 2171.34  158.27 2169.36   160.3 2168.39
   163.6 2167.76     170 2169.47   173.4 2170.16   183.1 2170.49   222.7 2169.53
   229.2 2170.43   248.9 2171.25     262 2170.42   278.5 2171.16   291.6 2170.58
   304.7 2173.36   341.1 2175.12   352.7 2177.14     399  2192.4   434.7 2202.33
   445.4 2204.37   459.7 2205.19   463.3  2206.2   470.4 2211.16   472.9 2212.51
#Mann= 5 ,-1 , 0
       0    .035       0  158.27    .045       0     170    .035       0
     240     .04       0  337.67      .1       0
#XS Ineff= 2 , 0
                          228.52         2173.34
Permanent Ineff=
       F       F
Bank Sta=158.27,170
XS Rating Curve= 0 ,0
Exp/Cntr=0.3,0.1

Type RM Length L Ch R = 1 ,305     ,168.1,170.2,169.1
XS GIS Cut Line= 3
2129160.17614682223182.1701340322129306.73510749223296.276753414
2129654.28921423223246.027966897
#Sta/Elev= 30
       0 2211.98    26.8 2206.91    58.8 2199.62    74.1 2195.23   112.2 2182.84
   120.4 2180.93   133.2 2180.27   154.9 2176.95   207.1 2173.24   223.2 2171.56
     267 2168.46   292.8 2168.06   301.7 2167.08     306 2166.72   309.3 2167.19
     316 2168.05   329.2 2168.12   345.8 2169.45   372.3 2169.44   392.2 2170.74
   448.6 2173.21   461.8 2176.54   481.7  2178.2     485    2179   488.4 2180.57
   498.3 2186.78   508.2 2192.13   511.6 2193.77   514.9  2194.8   536.9 2195.78
#Mann= 5 ,-1 , 0
       0    .035       0  295.74     .06       0   301.7    .045       0
   309.3     .06       0  395.74      .1       0
#XS Ineff= 2 , 0
                          332.37         2169.74
Permanent Ineff=
       F       F
Bank Sta=301.7,309.3
XS Rating Curve= 0 ,0
Exp/Cntr(USF)=0,0
Exp/Cntr=0.3,0.1

Type RM Length L Ch R = 1 ,135     ,34.8,40,42.5
XS GIS Cut Line= 4
2129113.06790946223412.4770722352129443.87242069223419.805020268
2129584.15028305 223371.649933192129667.89826058 223265.91811156
#Sta/Elev= 30
       0 2180.63    43.7 2179.78    95.7 2177.89   201.2 2172.36   217.6  2170.6
   286.5 2168.68   335.8 2168.34   349.9 2166.58   356.9 2164.87   360.3 2165.05
   364.2 2166.74   367.3 2167.32   374.2 2166.61   377.7 2165.33   381.1 2164.36
   388.1 2165.33   398.5 2168.86     421 2170.89   444.3 2171.06   483.1 2169.98
     499 2174.31   510.7 2179.18   528.3  2181.4   532.5 2182.85   538.7 2186.24
   553.4 2189.21     562 2192.27   567.6  2193.6   578.2 2195.12   614.1 2196.01
#Mann= 7 ,-1 , 0
       0      .1       0     110     .06       0   377.7    .045       0
   388.1     .06       0  410.89     .08       0   529.2     .06       0
   539.2      .1       0
#XS Ineff= 2 , 0
          308.55 2171.59   437.5         2171.27
Permanent Ineff=
       F       F
Bank Sta=377.7,388.1
XS Rating Curve= 0 ,0
Exp/Cntr(USF)=0,0
Exp/Cntr=0.5,0.3

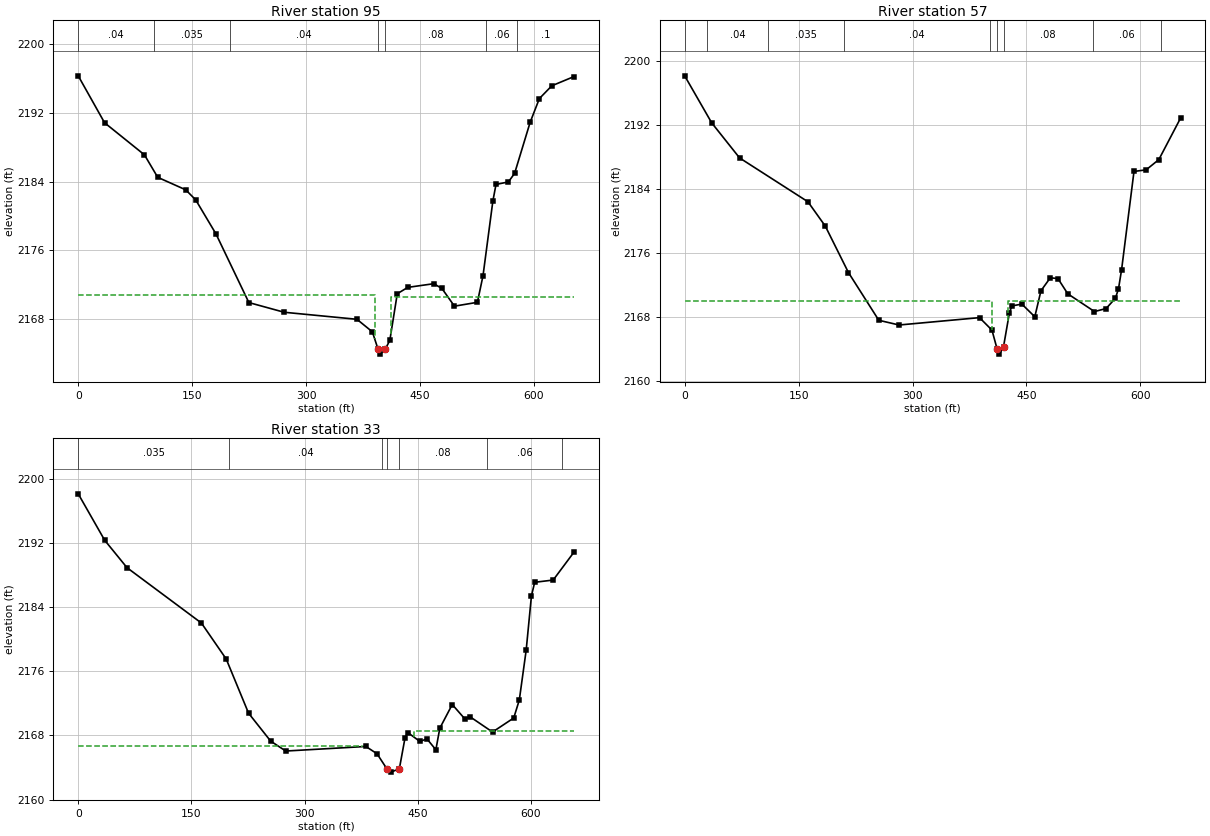
Type RM Length L Ch R = 1 ,95      ,40,38.3,38.3
XS GIS Cut Line= 4
2129119.34900777223496.2250497632129456.43461732223435.507766055
2129561.11958923223435.5077660552129683.60100637223270.105510437
#Sta/Elev= 30
       0 2196.32    34.7 2190.85    87.2 2187.11   104.7 2184.49   141.6 2183.03
   154.7 2181.86   181.4 2177.89   224.7 2169.89   271.2 2168.76     367 2167.94
   387.3 2166.48   394.6 2164.51   397.8 2163.88   404.4 2164.48   410.3 2165.48
   420.1 2170.92   433.9 2171.66   468.2 2172.09   478.9 2171.53   495.4 2169.47
   525.6 2169.92     533 2173.02     546 2181.74   550.1 2183.66   566.4 2183.95
   574.6 2184.95     595 2190.89   607.2 2193.67   623.6 2195.16     653 2196.24
#Mann= 7 ,-1 , 0
       0     .04       0     100    .035       0     200     .04       0
   394.6    .045       0   404.4     .08       0   537.2     .06       0
   577.2      .1       0
#XS Ineff= 2 , 0
          390.34 2170.79  411.69         2170.53
Permanent Ineff=
       F       F
Bank Sta=394.6,404.4
XS Rating Curve= 0 ,0
Exp/Cntr(USF)=0,0
Exp/Cntr=0.5,0.3

Type RM Length L Ch R = 1 ,57      ,22.9,23.1,22.9
XS GIS Cut Line= 4
 2129115.1616089223532.8647899312129452.24721845223472.147506223
2129556.93219036223472.1475062232129679.41360749223306.745250605
#Sta/Elev= 30
       0  2198.2    35.6 2192.32    72.3 2187.94   162.3 2182.46   185.2 2179.41
   215.6 2173.62   255.6 2167.65   282.3 2167.06   388.2 2167.98   404.6 2166.42
   411.2 2164.12   414.5 2163.42   419.8 2164.34   427.6  2168.6   430.9 2169.45
     444 2169.67     461 2168.09   469.1 2171.34   481.4 2172.96   491.5 2172.86
   504.4 2170.96   539.6 2168.74   554.9 2169.12   567.1  2170.4   571.2 2171.58
   575.3 2173.99   591.6 2186.25   607.6 2186.45   624.3 2187.73     653 2192.93
#Mann= 9 ,-1 , 0
       0    .035       0      30     .04       0     110    .035       0
     210     .04       0  402.51     .08       0   411.2    .045       0
   419.8     .08       0   537.2     .06       0   627.2      .1       0
#XS Ineff= 2 , 0
           404.2    2170   425.8            2170
Permanent Ineff=
       F       F
Bank Sta=411.2,419.8
XS Rating Curve= 0 ,0
Exp/Cntr(USF)=0,0
Exp/Cntr=0.5,0.3

Type RM Length L Ch R = 1 ,33      ,,,
XS GIS Cut Line= 4
 2129115.1616089223540.1927379652129486.79325918223516.115194426
2129556.93219036223479.4754542572129679.41360749223314.073198639
#Sta/Elev= 30
       0 2198.12    35.1 2192.33    64.7 2188.91   163.3 2182.01   196.2 2177.52
   225.8 2170.77   255.1 2167.29   275.1 2166.05   381.3 2166.62   396.1 2165.71
   409.3 2163.81   414.6 2163.42   425.7 2163.84   433.1 2167.64   436.8 2168.36
     453 2167.24   462.2 2167.57   474.1 2166.21   479.3 2168.89   495.8 2171.85
   512.3 2170.08   519.3 2170.33   549.2 2168.42   577.3 2170.17   584.7 2172.41
   593.8 2178.62   600.8 2185.41   605.1 2187.09   629.6 2187.37   657.4 2190.88
#Mann= 7 ,-1 , 0
       0    .035       0     200     .04       0  402.41     .08       0
   409.3    .045       0   425.7     .08       0  541.54     .06       0
  641.54      .1       0
#XS Ineff= 2 , 0
          376.42 2166.69  444.59         2168.53
Permanent Ineff=
       F       F
Bank Sta=409.3,425.7
XS Rating Curve= 0 ,0
Exp/Cntr(USF)=0,0
Exp/Cntr=0.3,0.1
LCMann Table=0

Chan Stop Cuts=-1
Use User Specified Reach Order=0
Composite Channel Slope=5